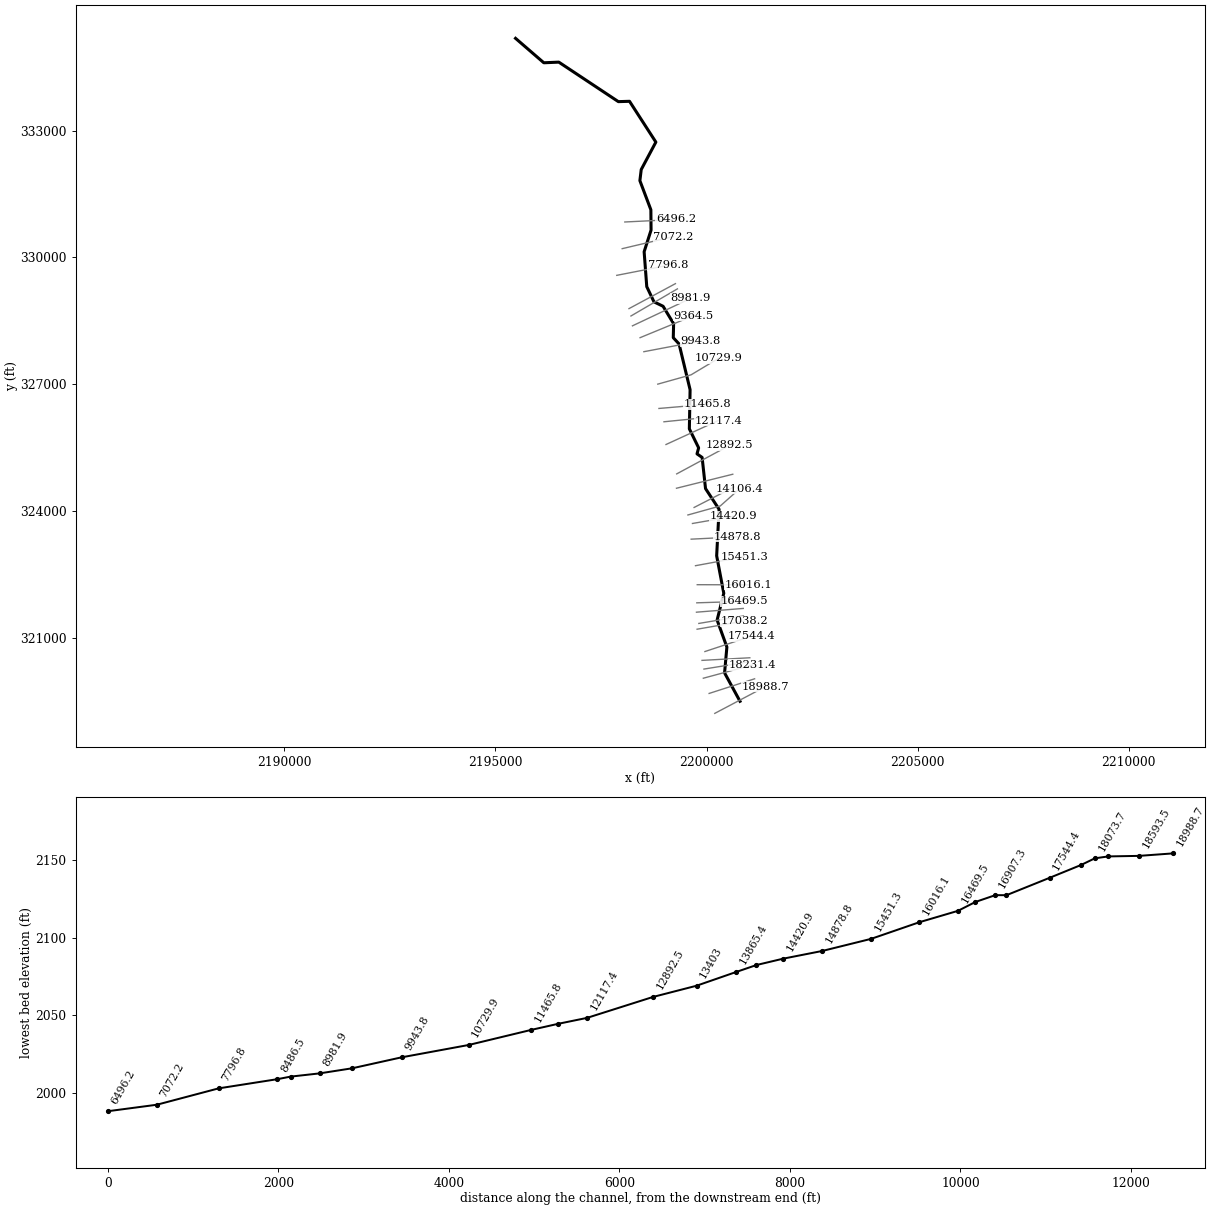
--- AntCkT2.prj (project) ---

Proj Title=AntCkT2
Current Plan=p01
Default Exp/Contr=0,0
English Units
Geom File=g01
Flow File=f01
Plan File=p01
BEGIN DESCRIPTION:
END DESCRIPTION:
DSS Export Rating Curves= 0
DSS Export Rating Curve Sorted= 0
DSS Export Volume Flow Curves= 0
DXF OffsetX= 0
DXF OffsetY= 0
DXF ScaleX= 0
DXF ScaleY= 0

--- AntCkT2.p01 (plan) ---

Plan Title=Floodplain
Program Version=4.00
Geom File=g01
Flow File=f01
K Sum by GR=0
Std Step Tol=0.01
Critical Tol=0.01
Num of Std Step Trials=20
Max Error Tol=0.3
Flow Tol Ratio=0.001
Split Flow NTrial=30
Split Flow Tol=0.02
Split Flow Ratio=0.02
Log Output Level=0
Friction Slope Method=1
Unsteady Friction Slope Method=2
Unsteady Bridges Friction Slope Method=1
Global Log Level=0
CheckData=False
Run HTab=0
Run UNet=0
Run PostProcess=0
UNET Theta=0
UNET Theta Warmup=0
UNET ZTol=0
UNET ZSATol=0
UNET MxIter=0
UNET MaxInSteps=0
UNET DtIC=0
UNET DtMin=0
UNET MaxCRTS=0
UNET WFStab=0
UNET SFStab=0
UNET WFX=0
UNET SFX=0
UNET DSS MLevel=0
UNET DZMax Abort=0
UNET Convert EG Bridges=0
UNET Use Existing IB Tables=0
UNET Froude Limit=0
UNET Froude Power=0
Write IC File=0
Echo Input=False
Echo Output=False
Write Detailed=0

--- AntCkT2.f01 (steady flow) ---

Flow Title=NFF Regression Equation
Program Version=4.00
Number of Profiles=1
Profile Names=P100yr
River Rch & RM=AntCkT2,Main      ,18988.7
390.9595
River Rch & RM=AntCkT2,Main      ,18593.5
586.3125
River Rch & RM=AntCkT2,Main      ,15451.3
631.9794
River Rch & RM=AntCkT2,Main      ,10729.9
698.0248
River Rch & RM=AntCkT2,Main      ,9943.8
1161.573
River Rch & RM=AntCkT2,Main      ,4185.6
1250.289
River Rch & RM=AntCkT2,Main      ,3673.1
1391.015
River Rch & RM=AntCkT2,Main      ,683
1424.830
Boundary for River Rch & Prof#=AntCkT2,Main      ,1
Up Type=0
Dn Type=3
Dn Slope=0.006012

--- AntCkT2.g01 (geometry) ---

Geom Title=USGS 10m DEM
Program Version=4.10

River Reach=AntCkT2         ,Main
Reach XY= 30
     2200793.523      319492.459     2200427.895      320165.038
     2200482.591      320776.933     2200251.336      321414.334
     2200409.148      322048.708     2200240.398      322936.013
      2200297.82      324036.404     2199976.726      324527.419
     2199895.867      325264.529     2199775.164      325348.904
     2199813.836      325490.701     2199593.523      325940.701
     2199611.101      326867.654     2199349.773      327950.466
     2199212.664      328098.122     2199220.867      328429.763
     2198971.257      328842.263     2198755.633       328946.56
     2198584.539      329306.326      2198522.43      330132.498
     2198686.492      330645.779     2198681.804      331126.248
     2198421.648       331815.31     2198453.289       332077.81
     2198800.164      332728.201     2198176.007      333693.665
     2197911.883      333685.622     2196500.945      334620.779
     2196145.867      334605.544     2195476.067       335184.01

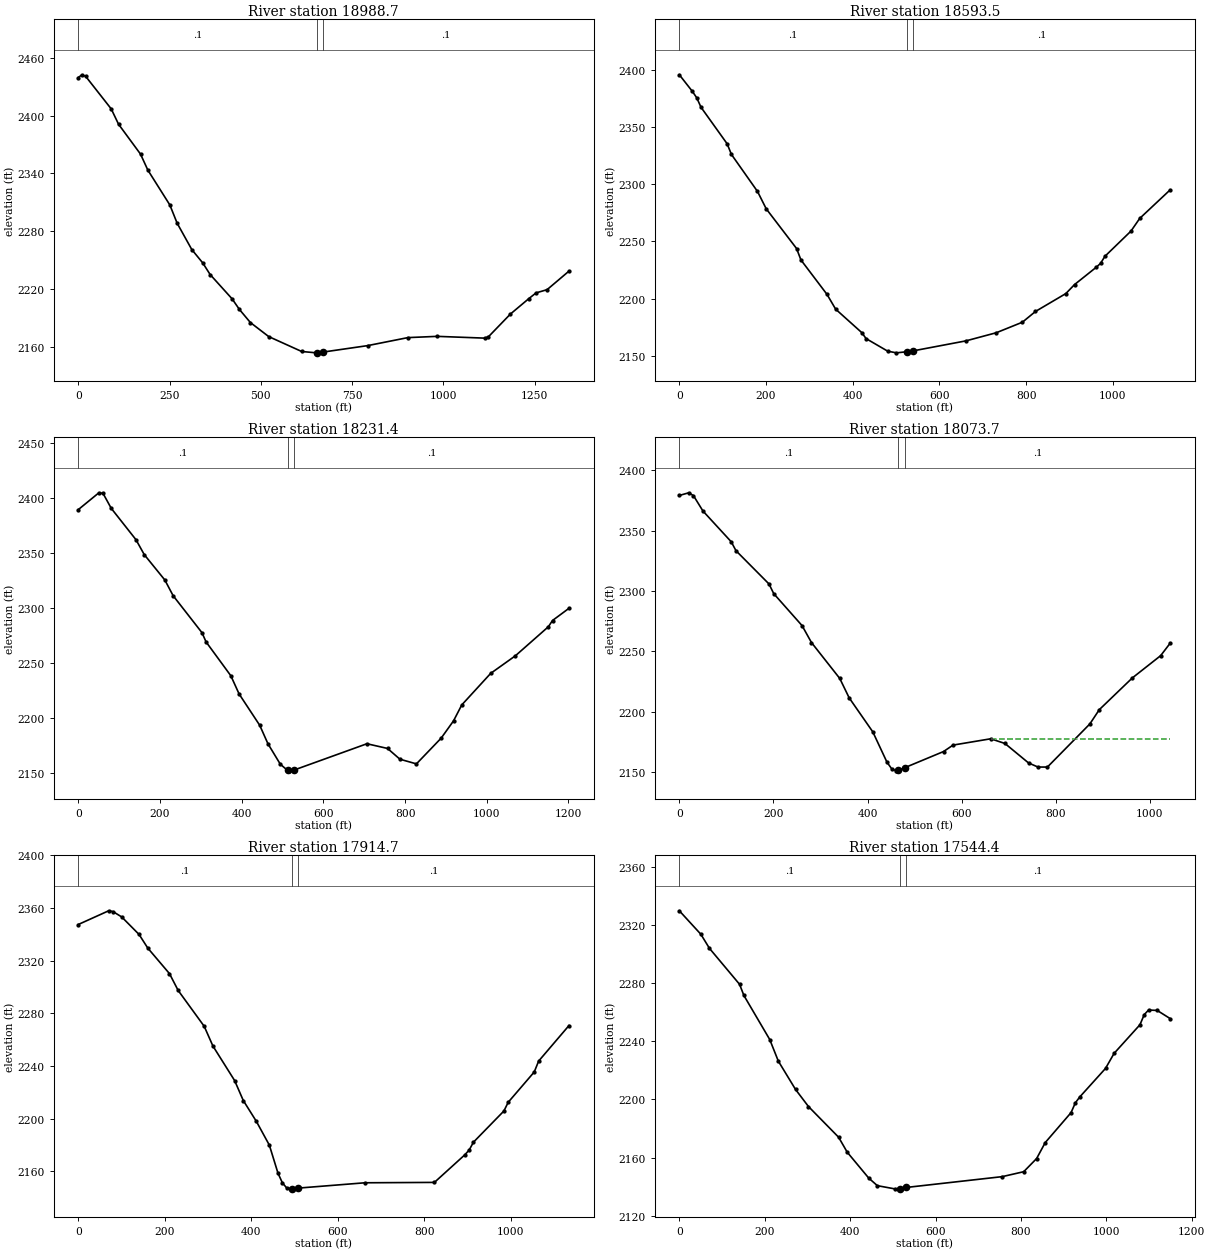
Type RM Length L Ch R = 1 ,18988.7 ,399.3,395.2,391.2
XS GIS Cut Line= 2
     2200196.012      319206.371     2201384.768       319833.54
#Sta/Elev= 30
       0 2439.36      10 2442.21    20.1 2440.68    90.3 2406.85   110.3 2391.01
   170.5 2360.03   190.6 2343.46   250.8 2307.38   270.8 2288.48   310.9 2261.19
     341  2247.3   361.1 2235.34   421.3 2210.14   441.3 2199.17   471.4 2185.59
   521.6 2171.04   611.8 2155.62     652 2154.21   653.9 2154.26   668.9 2154.92
   792.4 2161.68   902.7 2169.98     983 2171.28  1113.4 2169.44  1123.4 2170.88
  1183.6 2194.42  1233.7 2210.29  1253.8 2216.32  1283.9 2219.63    1344 2238.88
#Mann= 3 , 0 , 0
       0      .1       0   653.9    .045       0   668.9      .1       0
Bank Sta=653.9,668.9
XS Rating Curve= 0 ,0
Exp/Cntr=0.3,0.1

Type RM Length L Ch R = 1 ,18593.5 ,363.2,362,360.9
XS GIS Cut Line= 2
      2200061.83      319678.207     2201139.461      320024.834
#Sta/Elev= 30
       0 2395.68      30 2381.21    40.1 2375.58    50.1 2367.23   110.2  2335.4
   120.2 2326.04   180.3  2293.7   200.4 2278.53   270.5 2243.78   280.5 2233.82
   340.6 2203.73   360.6 2190.79   420.8 2170.31   430.8 2165.06   480.8 2154.04
   500.9 2152.62   524.2 2153.55   539.2 2154.34   661.2 2163.09   731.3 2170.21
   791.4 2179.41   821.5 2188.79   891.6 2204.44   911.6 2212.28   961.7 2227.42
   971.7 2230.87   981.7    2237  1041.8 2259.04  1061.9  2270.1    1132 2295.01
#Mann= 3 , 0 , 0
       0      .1       0   524.2    .045       0   539.2      .1       0
Bank Sta=524.2,539.2
XS Rating Curve= 0 ,0
Exp/Cntr=0.3,0.1

Type RM Length L Ch R = 1 ,18231.4 ,160.1,157.7,155.4
XS GIS Cut Line= 2
     2199924.552      320038.562      2201084.55      320350.869
#Sta/Elev= 30
       0 2389.72    50.5 2405.05    60.6 2404.52    80.8 2390.87   141.3 2362.37
   161.5 2348.85     212 2325.72   232.2  2311.5   302.8 2277.88   312.9 2269.46
   373.5  2238.7   393.7 2222.17   444.2 2193.67   464.4 2176.83   494.6  2158.3
   512.6 2152.59   514.8 2152.27   527.6 2152.91   706.6  2176.9   757.1 2172.62
   787.4 2162.83   827.8  2158.6   888.4 2182.03   918.6  2197.7   938.8  2212.2
  1009.5 2240.85  1070.1 2256.88  1150.8 2283.28  1160.9 2288.94  1201.3 2300.05
#Mann= 3 , 0 , 0
       0      .1       0   512.6    .045       0   527.6      .1       0
Bank Sta=512.6,527.6
XS Rating Curve= 0 ,0
Exp/Cntr=0.3,0.1

Type RM Length L Ch R = 1 ,18073.7 ,161.4,159,156.7
XS GIS Cut Line= 2
       2199939.4      320255.075      2200969.19      320420.789
#Sta/Elev= 30
       0 2379.31    20.1 2381.53    30.1 2379.13    50.2 2366.41   110.3 2340.91
   120.4  2333.5   190.6 2305.92   200.6 2297.94   260.8 2271.43   280.8  2257.4
     341 2227.59     361  2211.5   411.2 2183.32   441.3 2158.19   451.3 2152.72
   461.3 2151.02     465 2151.46     480 2153.78   561.6 2167.03   581.7 2172.36
   661.9  2177.6     692 2173.71   742.2 2157.56   762.2 2154.17   782.3 2154.15
   872.5  2189.9   892.6 2201.74   962.8 2228.05    1023 2246.52    1043 2256.74
#Mann= 3 , 0 , 0
       0      .1       0     465    .045       0     480      .1       0
#XS Ineff= 2 , 0
                          662.54         2177.73
Permanent Ineff=
       F       F
Bank Sta=465,480
XS Rating Curve= 0 ,0
Exp/Cntr=0.3,0.1

Type RM Length L Ch R = 1 ,17914.7 ,364.1,370.2,376.4
XS GIS Cut Line= 2
     2199893.665      320460.691     2201026.207      320522.466
#Sta/Elev= 30
       0 2347.51    70.3 2357.94    80.3 2357.32   100.4 2353.26   140.5 2339.97
   160.6 2329.64   210.8 2310.21   230.9 2297.43   291.1  2270.2   311.2 2255.24
   361.4    2229   381.4 2213.86   411.5 2198.09   441.6    2180   461.7 2158.57
   471.8 2151.32   481.8 2147.44   491.8 2146.79   493.5 2146.85   508.5 2147.35
   662.5 2151.39   823.1 2151.68   893.3 2172.59   903.4 2176.24   913.4 2182.24
   983.7  2205.9   993.7 2212.53  1053.9 2235.56    1064  2243.8  1134.2 2270.82
#Mann= 3 , 0 , 0
       0      .1       0   493.5    .045       0   508.5      .1       0
Bank Sta=493.5,508.5
XS Rating Curve= 0 ,0
Exp/Cntr=0.3,0.1

Type RM Length L Ch R = 1 ,17544.4 ,510,506.2,502.5
XS GIS Cut Line= 2
     2199962.304       320670.04     2201053.662      321030.394
#Sta/Elev= 30
       0 2329.89    50.4 2313.73    70.6    2304   141.1 2279.26   151.2 2271.58
   211.7 2241.28   231.9 2226.36   272.2 2206.88   302.4 2195.15     373 2174.02
   393.2  2163.7   443.6 2145.87   463.8 2140.66   504.1 2138.48   516.1 2138.67
   531.1 2139.42   756.1 2146.87   806.5 2150.27   836.8 2159.36   856.9 2170.32
   917.4 2190.95   927.5 2197.71   937.6 2201.67   998.1 2221.38  1018.2 2231.74
  1078.7 2251.42  1088.8 2258.41  1098.9 2261.57  1119.1  2261.3  1149.3 2255.71
#Mann= 3 , 0 , 0
       0      .1       0   516.1    .045       0   531.1      .1       0
Bank Sta=516.1,531.1
XS Rating Curve= 0 ,0
Exp/Cntr=0.3,0.1

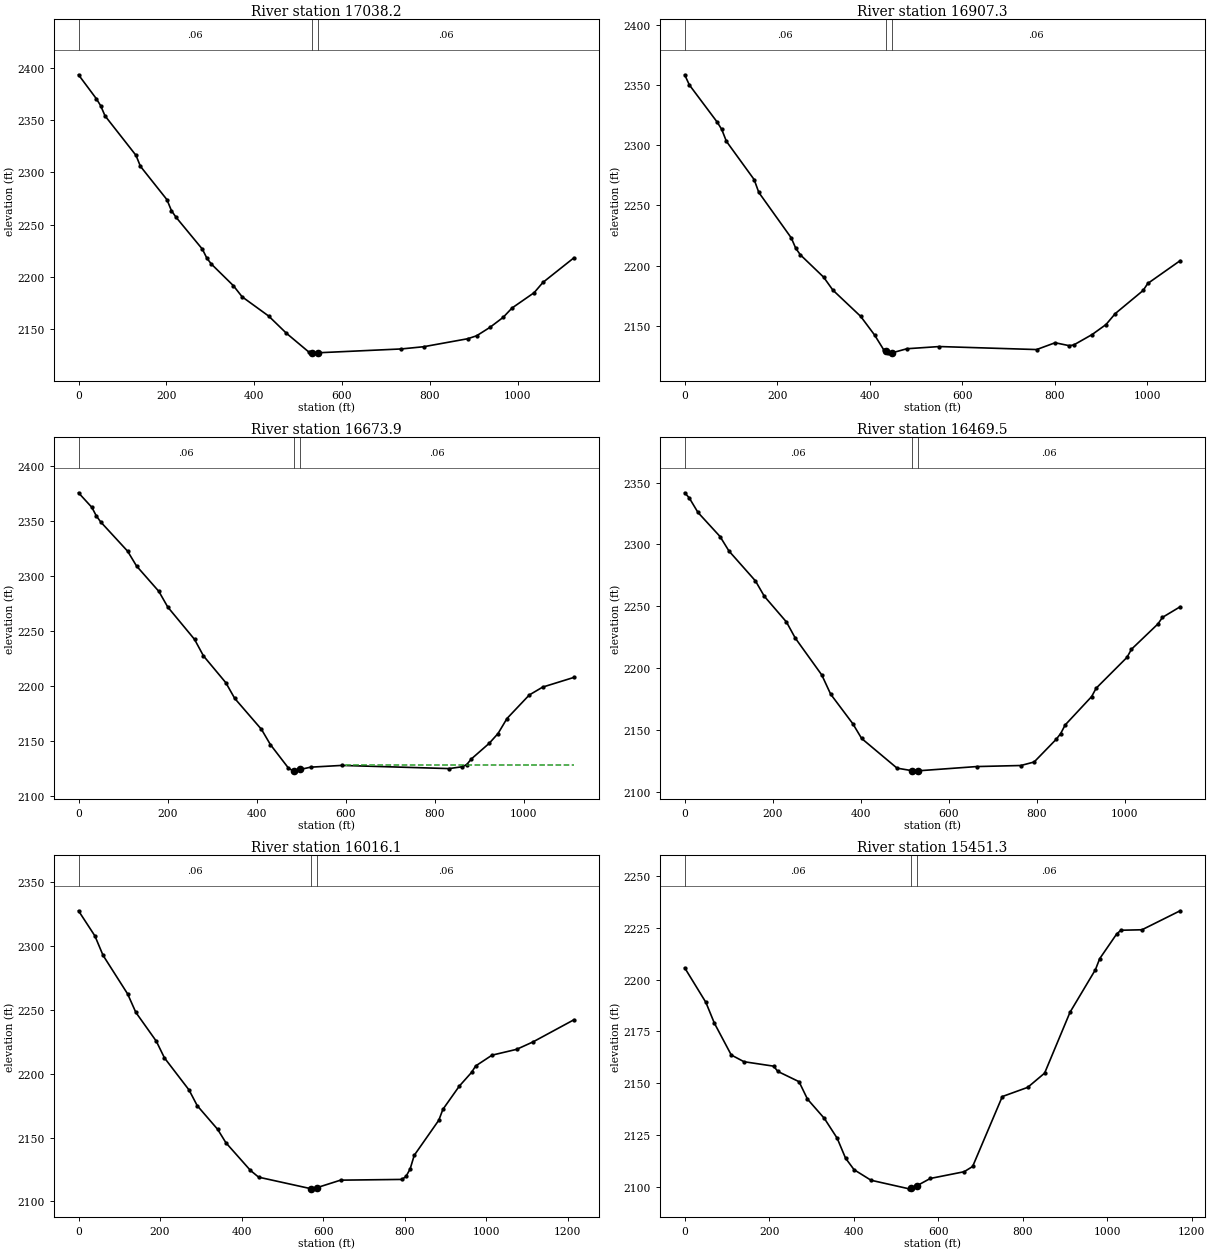
Type RM Length L Ch R = 1 ,17038.2 ,131,130.9,130.9
XS GIS Cut Line= 2
     2199776.979      321198.559     2200888.929      321390.748
#Sta/Elev= 30
       0 2393.51    40.3 2370.77    50.4 2363.97    60.4 2354.19     131 2316.33
     141  2305.9   201.5  2273.9   211.6  2263.5   221.7 2257.35   282.1 2226.58
   292.2 2218.07   302.3 2212.42   352.6 2191.66   372.8 2180.89   433.2 2162.48
   473.5 2146.06   523.9 2128.31   531.5 2127.53     534 2127.28   546.5 2127.35
   735.5 2131.02   785.9 2133.12   886.6 2140.79   906.8 2143.62     937 2151.63
   967.2 2161.23   987.4 2170.18  1037.8 2184.87  1057.9 2194.73  1128.4 2218.26
#Mann= 3 , 0 , 0
       0     .06       0   531.5    .045       0   546.5     .06       0
Bank Sta=531.5,546.5
XS Rating Curve= 0 ,0
Exp/Cntr=0.3,0.1

Type RM Length L Ch R = 1 ,16907.3 ,235,233.1,231.3
XS GIS Cut Line= 2
     2199818.075      321335.171     2200874.497      321512.721
#Sta/Elev= 30
       0 2358.86      10 2350.44    70.1 2319.52    80.1 2313.36    90.1 2303.49
   150.2 2271.56   160.2 2260.89   230.3 2223.09   240.3 2214.22   250.3 2208.84
   300.4 2190.32   320.4 2179.53   380.4  2157.7   410.5 2142.18   430.5 2129.72
   434.3  2128.8   440.5  2127.3   449.3 2127.41   480.6 2130.72   550.6 2132.54
   760.9 2130.03   800.9  2135.7     831  2133.3     841 2133.82     881 2142.56
     911 2150.88   931.1 2160.04   991.2 2179.24  1001.2 2185.06  1071.2 2204.04
#Mann= 3 , 0 , 0
       0     .06       0   434.3    .045       0   449.3     .06       0
#XS Ineff= 2 , 0
                          560.82         2132.27
Permanent Ineff=
       F       F
Bank Sta=434.3,449.3
XS Rating Curve= 0 ,0
Exp/Cntr=0.3,0.1

Type RM Length L Ch R = 1 ,16673.9 ,204.3,204.6,204.9
XS GIS Cut Line= 2
      2199761.85      321601.496     2200871.538      321690.271
#Sta/Elev= 30
       0 2375.35    30.1 2362.07    40.1 2354.32    50.2 2348.73   110.3 2322.36
   130.4 2308.89   180.5 2285.86   200.6  2271.6   260.8 2242.23   280.8 2227.27
     331 2202.95     351  2188.7   411.2 2160.54   431.2 2146.75   471.4 2125.61
   481.4 2122.92   483.4 2122.95   498.4 2124.18   521.5 2126.25   591.7 2127.85
   832.4 2124.97   862.5 2126.63   872.5 2128.67   882.6 2133.66   922.7 2147.84
   942.7 2156.78   962.8 2170.42  1012.9 2191.79    1043 2198.95  1113.2 2207.74
#Mann= 3 , 0 , 0
       0     .06       0   483.4    .045       0   498.4     .06       0
#XS Ineff= 2 , 0
                          602.06         2128.09
Permanent Ineff=
       F       F
Bank Sta=483.4,498.4
XS Rating Curve= 0 ,0
Exp/Cntr=0.3,0.1

Type RM Length L Ch R = 1 ,16469.5 ,455.7,453.4,451
XS GIS Cut Line= 2
     2199770.115      321823.173     2200895.793      321857.493
#Sta/Elev= 30
       0 2341.77    10.1 2337.76    30.2 2325.87    80.4 2306.41   100.6 2294.75
   160.9 2270.55     181 2258.18   231.3 2237.41   251.4 2224.38   311.7 2194.57
   331.8 2179.11   382.1 2155.28   402.2 2143.34   482.7 2119.37   515.6 2117.39
   522.9 2117.19   530.6 2117.21   663.6 2120.64   764.2  2121.5   794.4 2124.34
   844.6 2142.71   854.7 2147.31   864.8  2154.2   925.1 2177.19   935.2 2183.88
  1005.5 2208.87  1015.6 2215.39  1075.9 2235.88    1086 2241.13  1126.2 2249.68
#Mann= 3 , 0 , 0
       0     .06       0   515.6    .045       0   530.6     .06       0
Bank Sta=515.6,530.6
XS Rating Curve= 0 ,0
Exp/Cntr=0.3,0.1

Type RM Length L Ch R = 1 ,16016.1 ,560.2,564.8,569.4
XS GIS Cut Line= 2
     2199780.411      322252.166     2200995.319      322248.735
#Sta/Elev= 30
       0  2327.7    40.2 2308.01    60.2 2292.79   120.5 2262.54   140.6  2248.1
   190.8 2225.52   210.8 2212.43   271.1 2187.28   291.2 2174.99   341.4  2156.4
   361.5 2145.96   421.7 2124.26   441.8 2118.99   570.9 2109.89   572.3 2109.85
   585.9 2110.89   642.6 2116.65   793.2 2117.23   803.2  2119.6   813.3 2125.46
   823.3  2136.1   883.6 2163.63   893.6 2172.12   933.8 2190.31   963.9 2201.08
   973.9 2206.12  1014.1 2214.58  1074.4 2219.14  1114.5 2224.95  1214.9  2242.3
#Mann= 3 , 0 , 0
       0     .06       0   570.9    .045       0   585.9     .06       0
Bank Sta=570.9,585.9
XS Rating Curve= 0 ,0
Exp/Cntr=0.3,0.1

Type RM Length L Ch R = 1 ,15451.3 ,575.4,572.5,569.6
XS GIS Cut Line= 2
     2199739.227      322701.751     2200892.361      322914.532
#Sta/Elev= 30
       0 2205.67    50.1 2189.03    70.2 2179.01   110.2 2163.66   140.3 2160.42
   210.5 2158.27   220.5 2155.73   270.6 2150.79   290.6 2142.38   330.7 2133.05
   360.8 2123.57   380.8 2113.89   400.9 2108.36     441 2103.28   531.2 2099.14
   535.4 2099.35   550.4 2100.72   581.3 2104.14   661.5 2107.39   681.5 2109.92
   751.7 2143.62   811.8 2148.05   851.9 2154.92     912 2184.26   972.2  2204.8
   982.2 2210.07  1022.3 2221.95  1032.3 2223.78  1082.4 2224.02  1172.6 2233.17
#Mann= 3 , 0 , 0
       0     .06       0   535.4    .045       0   550.4     .06       0
Bank Sta=535.4,550.4
XS Rating Curve= 0 ,0
Exp/Cntr=0.3,0.1

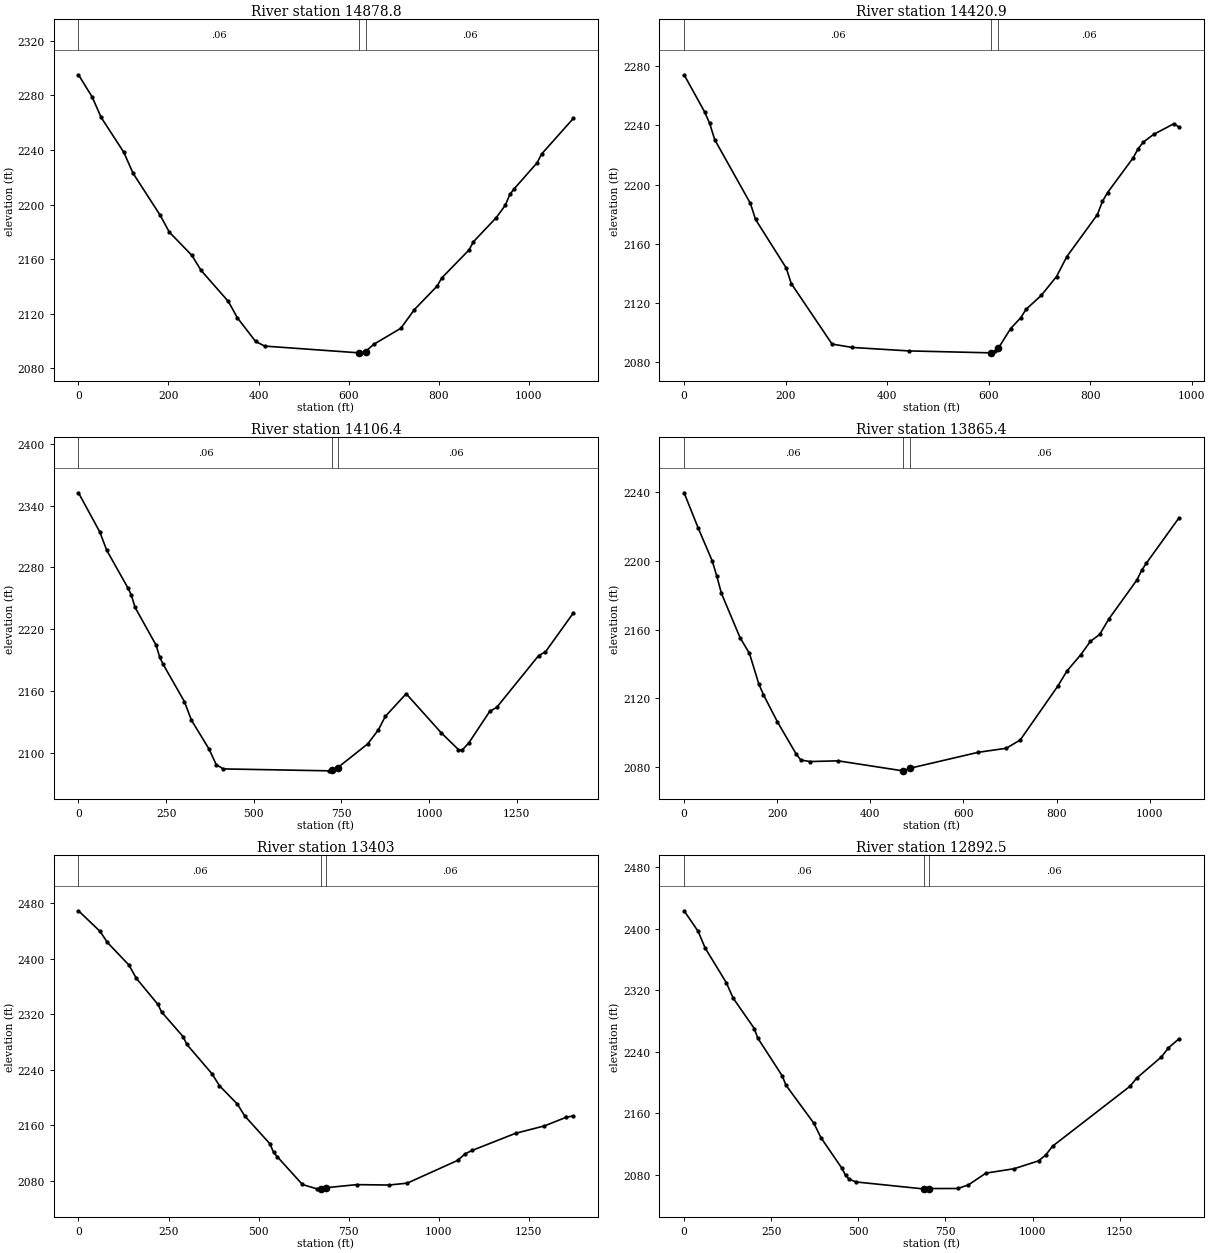
Type RM Length L Ch R = 1 ,14878.8 ,454.7,457.8,460.9
XS GIS Cut Line= 2
     2199636.269      323329.797     2200734.491      323384.709
#Sta/Elev= 30
       0 2295.14    30.3 2278.97    50.4 2263.89   100.9 2238.22   121.1 2223.07
   181.6 2192.14   201.8 2179.84   252.2 2162.69   272.4 2151.76   332.9 2129.04
   353.1    2117   393.4 2099.74   413.6 2096.29   622.9 2091.35   625.5 2091.34
   637.9 2092.27   655.7 2097.52   716.2 2109.32   746.5 2123.08     797  2140.3
     807 2146.18   867.6  2166.7   877.7 2172.82   928.1 2190.38   948.3 2199.48
   958.4  2207.4   968.4 2211.68  1018.9 2230.63    1029 2237.05  1099.6 2263.18
#Mann= 3 , 0 , 0
       0     .06       0   622.9    .045       0   637.9     .06       0
Bank Sta=622.9,637.9
XS Rating Curve= 0 ,0
Exp/Cntr=0.3,0.1

Type RM Length L Ch R = 1 ,14420.9 ,311.8,314.4,316.9
XS GIS Cut Line= 2
     2199667.125      323700.884     2200627.796      323868.135
#Sta/Elev= 30
       0 2274.17    40.2 2249.24    50.3 2241.42    60.3 2230.36   130.7 2187.24
   140.7  2176.5   201.1 2143.75   211.1 2133.18   291.5  2092.3   331.7 2090.01
   442.3 2087.69   603.2 2086.38   604.3 2086.48   613.2 2087.32   619.3 2089.57
   643.4  2102.8   663.5 2110.14   673.5  2115.7   703.7 2125.16   733.8  2137.9
     754 2151.32   814.3 2179.73   824.3 2188.72   834.4 2194.64   884.6    2218
   894.7 2224.25   904.8 2228.71   924.9 2233.85   965.1 2241.13   975.1 2238.85
#Mann= 3 , 0 , 0
       0     .06       0   604.3    .045       0   619.3     .06       0
Bank Sta=604.3,619.3
XS Rating Curve= 0 ,0
Exp/Cntr=0.3,0.1

Type RM Length L Ch R = 1 ,14106.4 ,235.7,241.1,246.5
XS GIS Cut Line= 3
     2199559.545       323902.38      2200326.09      324115.713
     2200787.175      324524.266
#Sta/Elev= 30
       0 2352.41    60.4 2314.63    80.6 2296.58     141 2259.97   151.1 2252.77
   161.2 2241.22   221.6 2204.25   231.6 2192.76   241.7 2185.64   302.2 2149.52
   322.3 2131.45   372.7 2103.28   392.8 2088.36     413 2084.15   715.1 2082.27
   724.6 2082.71   739.6 2085.37   825.5  2108.6   855.3 2122.01   875.2 2135.14
   934.8 2157.17  1034.2 2119.43  1083.8 2102.94  1093.8 2102.18  1113.6 2109.45
  1173.2 2140.11  1193.1 2143.93  1312.4 2194.17  1332.2  2197.9  1411.7 2235.68
#Mann= 3 , 0 , 0
       0     .06       0   724.6    .045       0   739.6     .06       0
Bank Sta=724.6,739.6
XS Rating Curve= 0 ,0
Exp/Cntr=0.3,0.1

Type RM Length L Ch R = 1 ,13865.4 ,467.5,462.3,457
XS GIS Cut Line= 2
     2199705.983       324080.05     2200651.754      324565.355
#Sta/Elev= 30
       0 2239.64    30.1 2219.21    60.2  2200.1    70.2 2191.13    80.2 2181.04
   120.3 2155.21   140.4 2146.08   160.5 2128.27   170.5 2122.02   200.6 2106.18
   240.7 2087.52   250.7 2084.01   270.8 2083.14   330.9 2083.55   469.2 2077.75
   471.3 2077.73   484.2 2079.18   631.8 2088.52     692 2090.88     722  2095.7
   802.3 2126.91   822.3 2135.86   852.4 2145.47   872.5 2153.07   892.5 2157.12
   912.6 2166.26   972.8 2188.94   982.8 2194.48   992.8  2198.6    1063 2225.05
#Mann= 3 , 0 , 0
       0     .06       0   469.2    .045       0   484.2     .06       0
Bank Sta=469.2,484.2
XS Rating Curve= 0 ,0
Exp/Cntr=0.3,0.1

Type RM Length L Ch R = 1 ,13403   ,504.7,510.6,516.4
XS GIS Cut Line= 2
     2199288.542        324535.2     2200622.252      324866.577
#Sta/Elev= 30
       0 2468.63    60.2 2438.88    80.2 2423.15   140.4 2390.46   160.5 2371.64
   220.7 2334.01   230.7  2323.2   290.9 2287.49   300.9 2276.54   371.2 2234.06
   391.2 2217.32   441.4  2190.6   461.4 2173.92   531.6 2133.67   541.7 2121.35
   551.7 2115.28   621.9 2075.15     662 2068.91     673 2069.04     688 2070.57
   772.4 2074.95   862.7 2074.39   912.8 2077.08  1053.3 2109.86  1073.3 2119.12
  1093.4 2124.17  1213.8 2148.74    1294  2159.4  1354.2 2171.73  1374.3 2173.74
#Mann= 3 , 0 , 0
       0     .06       0     673    .045       0     688     .06       0
Bank Sta=673,688
XS Rating Curve= 0 ,0
Exp/Cntr=0.3,0.1

Type RM Length L Ch R = 1 ,12892.5 ,776.8,774.8,772.8
XS GIS Cut Line= 2
     2199293.582      324874.473     2200543.604      325548.819
#Sta/Elev= 30
       0 2423.22    40.3 2396.43    60.4 2374.83   120.9 2329.87     141 2309.52
   201.5 2270.08   211.5 2257.62     282  2208.3   292.1 2196.57   372.7 2146.78
   392.8 2128.17   453.3 2088.14   463.4 2079.14   473.4 2074.17   493.6 2070.64
     685 2061.68   687.2  2061.7   702.2 2062.07   785.7 2062.13   815.9 2066.82
   866.3 2082.12   946.9 2087.82  1017.4 2098.09  1037.5 2105.51  1057.7 2117.22
  1279.3 2194.91  1299.4 2205.85    1370 2233.27  1390.1 2245.02  1420.3 2256.75
#Mann= 3 , 0 , 0
       0     .06       0   687.2    .045       0   702.2     .06       0
Bank Sta=687.2,702.2
XS Rating Curve= 0 ,0
Exp/Cntr=0.3,0.1

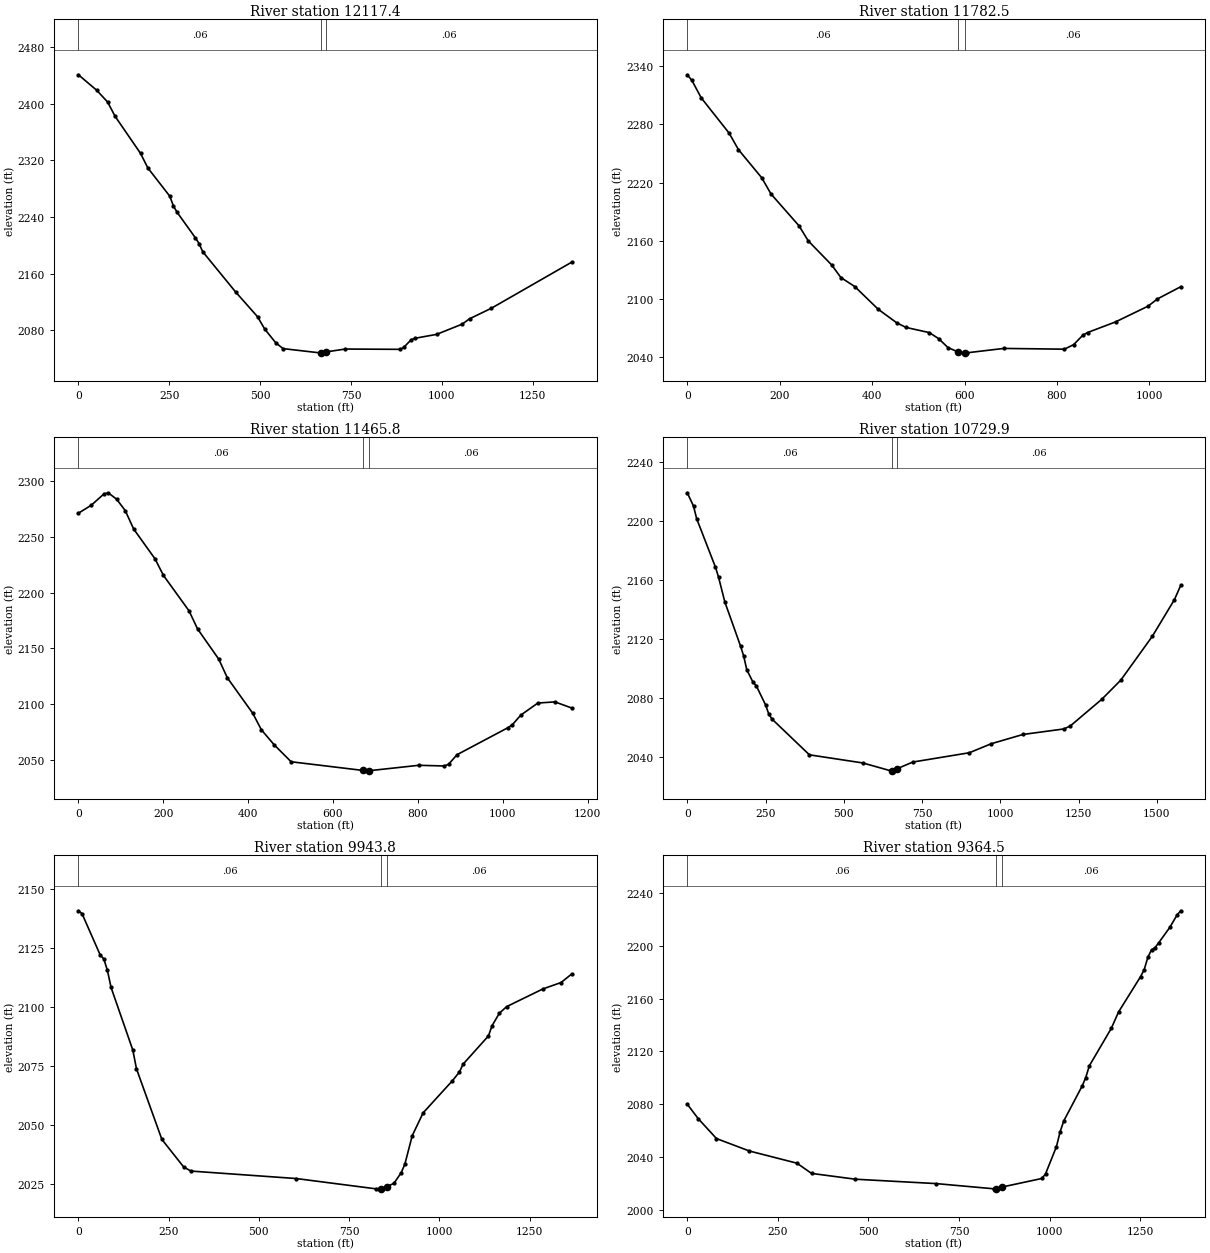
Type RM Length L Ch R = 1 ,12117.4 ,342.6,334.9,327.2
XS GIS Cut Line= 2
     2199040.297       325570.03     2200274.169      326135.943
#Sta/Elev= 30
       0 2440.92    50.3 2419.07    80.4  2402.4   100.6  2382.5   170.9 2329.93
     191 2309.33   251.4 2269.41   261.4 2255.56   271.5 2246.68   321.8 2210.62
   331.8 2202.59   341.9 2191.08   432.4  2134.2   492.7 2099.23   512.8 2081.51
     543  2062.3   563.1 2054.13   663.6 2048.17     666  2048.3     681 2049.46
     734 2053.53   884.9 2053.12   894.9 2055.81     915  2066.5   925.1 2068.66
   985.4 2074.26  1055.8 2088.72  1075.9 2096.24  1136.2  2111.2  1357.5 2176.37
#Mann= 3 , 0 , 0
       0     .06       0     666    .045       0     681     .06       0
Bank Sta=666,681
XS Rating Curve= 0 ,0
Exp/Cntr=0.3,0.1

Type RM Length L Ch R = 1 ,11782.5 ,317.1,316.8,316.4
XS GIS Cut Line= 2
     2198992.467      326108.307     2200054.808      326214.837
#Sta/Elev= 30
       0 2331.24    10.1 2325.39    30.2 2307.44    90.6 2271.02   110.8 2253.99
   161.2 2224.95   181.3 2208.21   241.7 2175.51   261.9 2159.82   312.2  2135.2
   332.4 2122.08   362.6 2112.71     413 2089.41   453.3 2075.34   473.4  2070.6
   523.8 2065.26   543.9 2059.05     564 2049.86   585.5 2045.41   600.5 2044.42
   604.3  2044.4   684.9 2048.95   815.9 2048.17     836 2052.87   856.2 2062.73
   866.2 2065.37   926.7 2076.32   997.2  2092.6  1017.3 2100.02  1067.7 2112.61
#Mann= 3 , 0 , 0
       0     .06       0   585.5    .045       0   600.5     .06       0
Bank Sta=585.5,600.5
XS Rating Curve= 0 ,0
Exp/Cntr=0.3,0.1

Type RM Length L Ch R = 1 ,11465.8 ,731.5,735.7,740
XS GIS Cut Line= 2
     2198873.037      326423.479     2200031.734      326522.578
#Sta/Elev= 30
       0 2270.98    30.1 2278.04    60.2 2288.21    70.2 2289.24    90.2 2283.44
   110.3 2273.34   130.3 2256.78   180.4 2230.21   200.5 2215.25   260.7 2183.61
   280.7  2167.5   330.8 2140.36   350.9 2123.75     411 2091.88   431.1 2077.23
   461.2 2063.81   501.3 2048.59   669.5 2040.88   681.7 2040.47   684.5 2040.55
     802 2045.43   862.2 2044.82   872.2 2046.29   892.2  2054.9  1012.6 2079.15
  1022.6 2081.74  1042.6 2090.37  1082.7 2101.12  1122.8 2102.16  1162.9 2096.63
#Mann= 3 , 0 , 0
       0     .06       0   669.5    .045       0   684.5     .06       0
Bank Sta=669.5,684.5
XS Rating Curve= 0 ,0
Exp/Cntr=0.3,0.1

Type RM Length L Ch R = 1 ,10729.9 ,787.5,785.7,784
XS GIS Cut Line= 3
      2198845.49      326999.121     2199635.496      327220.237
     2200283.816        327608.8
#Sta/Elev= 30
       0 2219.08      20 2210.08      30 2201.56      90 2168.73     100 2161.87
     120 2145.14   170.1  2115.3   180.1 2108.58   190.1 2099.23   210.1  2090.7
   220.1  2088.5   250.1  2075.4   260.1 2069.39   270.1 2065.91   390.2 2041.56
   560.2 2036.08   650.3 2030.72   655.1 2030.89   670.1 2032.12   720.3 2036.67
     901 2042.98   971.5 2049.12  1072.3 2055.36  1203.3 2059.11  1223.5 2061.13
  1324.3 2079.25  1384.7 2092.16  1485.5 2121.89    1556 2146.69  1576.2 2156.34
#Mann= 3 , 0 , 0
       0     .06       0   655.1    .045       0   670.1     .06       0
Bank Sta=655.1,670.1
XS Rating Curve= 0 ,0
Exp/Cntr=0.3,0.1

Type RM Length L Ch R = 1 ,9943.8  ,574.9,579.2,583.6
XS GIS Cut Line= 2
     2198516.154       327767.01     2199859.365      328021.479
#Sta/Elev= 30
       0 2140.58      10 2139.37    60.3 2121.89    70.4 2120.18    80.4  2115.3
    90.5 2108.08   150.8 2081.54   160.8 2073.67   231.2 2043.72   291.5 2032.06
   311.6  2030.3   603.1 2027.14   824.3 2022.77   838.6  2022.9   853.6 2023.55
   874.5 2025.17   894.6 2029.69   904.7 2033.41   924.8 2045.29     955 2054.97
  1035.4 2068.45  1055.5 2072.26  1065.5 2075.56  1135.9 2087.55    1146 2091.88
  1166.1 2097.16  1186.2 2099.96  1286.7 2107.46    1337 2110.18  1367.1 2113.85
#Mann= 3 , 0 , 0
       0     .06       0   838.6    .045       0   853.6     .06       0
Bank Sta=838.6,853.6
XS Rating Curve= 0 ,0
Exp/Cntr=0.3,0.1

Type RM Length L Ch R = 1 ,9364.5  ,381.9,382.6,383.2
XS GIS Cut Line= 2
     2198425.963      328098.787     2199685.424      328617.388
#Sta/Elev= 30
       0 2079.92    30.3 2068.91    80.7 2053.82   171.5 2044.39   302.7 2035.16
     343 2027.41   464.1 2023.01   686.1  2019.7   847.5 2015.71   853.3 2015.76
   868.3 2017.05   978.7 2023.56   988.8 2027.03    1019 2047.76  1029.1 2058.97
  1039.2 2067.23  1089.6 2093.51  1099.7 2099.96  1109.8 2109.02  1170.4 2137.43
  1190.5 2149.88  1251.1 2176.59  1261.2 2181.97  1271.2 2191.26  1281.3  2196.9
  1291.4 2198.68  1301.5 2202.38  1331.8 2213.93    1352 2223.43    1362 2226.53
#Mann= 3 , 0 , 0
       0     .06       0   853.3    .045       0   868.3     .06       0
Bank Sta=853.3,868.3
XS Rating Curve= 0 ,0
Exp/Cntr=0.3,0.1

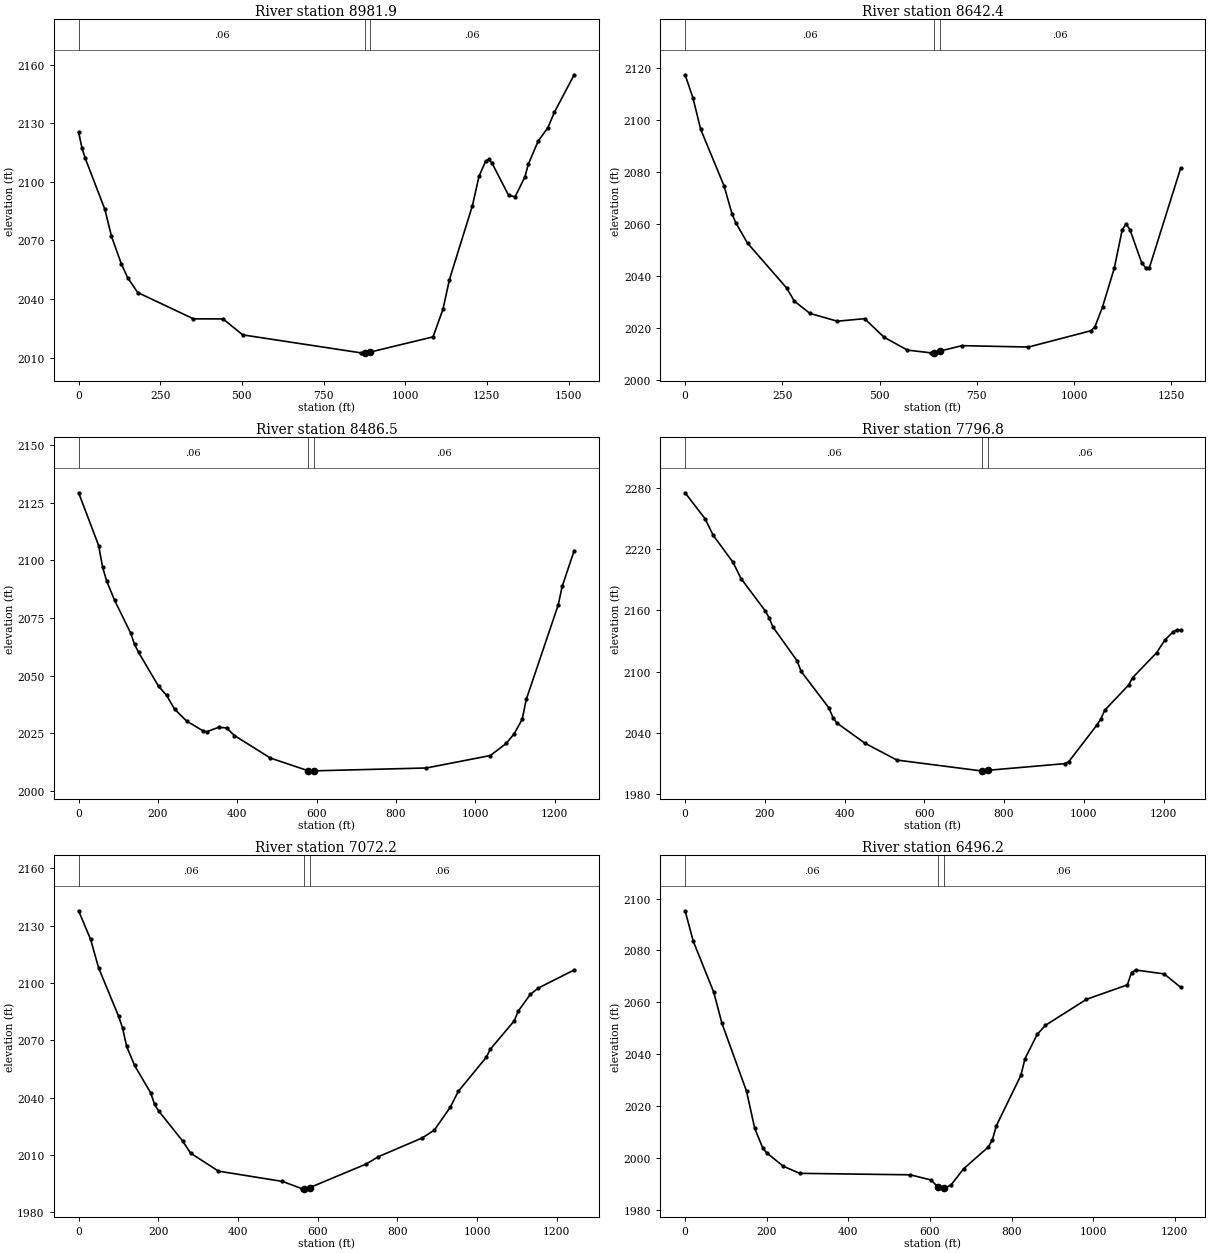
Type RM Length L Ch R = 1 ,8981.9  ,338.2,339.2,340.1
XS GIS Cut Line= 2
     2198245.579      328379.025     2199617.781      329026.472
#Sta/Elev= 30
       0 2125.37      10 2117.42    20.1 2112.07    80.4 2085.84   100.5 2072.12
   130.6 2058.04   150.7  2050.7   180.9  2043.3   351.7 2029.82   442.1 2029.78
   502.4 2021.62   864.1 2012.42   875.9 2012.44   890.9 2012.74  1085.2  2020.6
  1115.4 2034.64  1135.4 2049.94  1205.8 2087.81  1225.9  2102.8    1246 2110.45
    1256 2111.44  1266.1 2109.42  1316.3 2093.13  1336.4 2092.29  1366.6 2102.56
  1376.6 2108.87  1406.8 2120.76  1436.9  2127.7    1457 2135.67  1517.3 2154.77
#Mann= 3 , 0 , 0
       0     .06       0   875.9    .045       0   890.9     .06       0
Bank Sta=875.9,890.9
XS Rating Curve= 0 ,0
Exp/Cntr=0.3,0.1

Type RM Length L Ch R = 1 ,8642.4  ,155.9,156.1,156.3
XS GIS Cut Line= 2
     2198209.944       328612.11     2199310.478      329254.088
#Sta/Elev= 30
       0 2117.39    20.1 2108.54    40.1 2096.38   100.3 2074.57   120.4 2063.96
   130.4 2060.38   160.5 2052.58   260.8 2035.35   280.9 2030.24     321 2025.52
   391.3 2022.52   461.5  2023.5   511.6 2016.34   571.8 2011.39     632 2010.34
   639.9 2010.37   654.9 2011.01   712.3 2013.11   882.8 2012.57  1043.4 2018.84
  1053.4 2020.25  1073.4 2028.09  1103.5 2042.93  1123.6  2057.5  1133.6 2060.02
  1143.7 2057.79  1173.8 2045.06  1183.8 2043.16  1193.8 2043.14  1274.1 2081.43
#Mann= 3 , 0 , 0
       0     .06       0   639.9    .045       0   654.9     .06       0
Bank Sta=639.9,654.9
XS Rating Curve= 0 ,0
Exp/Cntr=0.3,0.1

Type RM Length L Ch R = 1 ,8486.5  ,696.6,689.4,682.2
XS GIS Cut Line= 2
     2198163.426      328786.495      2199263.94       329377.68
#Sta/Elev= 30
       0 2129.27    50.4  2106.4    60.4 2097.03    70.5 2091.09    90.7 2082.63
     131 2068.49     141 2063.53   151.1 2060.09   201.5 2045.35   221.6 2041.47
   241.8 2035.46     272 2030.32   312.3 2026.16   322.4 2025.61   352.6 2027.56
   372.8 2027.32   392.9 2023.99   483.6 2014.22   577.4  2008.8   592.4  2008.7
   594.4 2008.69   876.5 2009.93  1037.7 2015.32    1078 2020.58  1098.1 2024.81
  1118.3 2031.09  1128.4 2039.64    1209 2080.64    1219  2088.7  1249.2 2104.16
#Mann= 3 , 0 , 0
       0     .06       0   577.4    .045       0   592.4     .06       0
Bank Sta=577.4,592.4
XS Rating Curve= 0 ,0
Exp/Cntr=0.3,0.1

Type RM Length L Ch R = 1 ,7796.8  ,722.8,723.9,724.9
XS GIS Cut Line= 2
     2197873.952      329574.299     2199093.804      329812.551
#Sta/Elev= 30
       0 2275.24    50.1  2249.8    70.2 2233.77   120.3    2207   140.3 2191.18
   200.5 2159.78   210.5 2152.95   220.5 2143.57   280.7 2110.74   290.7 2100.43
   360.8 2064.34   370.9 2054.87   380.9 2049.55     451 2029.84   531.2 2013.32
   741.7 2002.75   745.5 2002.84   760.5 2003.31   952.2  2009.8   962.2 2011.68
  1032.4 2047.38  1042.4 2053.23  1052.5 2062.17  1112.6 2086.88  1122.6 2094.09
  1182.8 2118.56  1202.8 2130.64  1222.8 2138.56  1232.9 2140.79  1242.9 2140.48
#Mann= 3 , 0 , 0
       0     .06       0   745.5    .045       0   760.5     .06       0
Bank Sta=745.5,760.5
XS Rating Curve= 0 ,0
Exp/Cntr=0.3,0.1

Type RM Length L Ch R = 1 ,7072.2  ,580.9,575.9,570.9
XS GIS Cut Line= 2
     2198002.608      330205.668     2199212.931      330491.571
#Sta/Elev= 30
       0 2137.77    30.1 2122.74    50.2 2107.84   100.3 2082.53   110.3 2076.33
   120.4 2066.82   140.4  2056.8   180.5 2042.56   190.6 2036.46   200.6 2033.05
   260.8 2017.31   280.8 2010.93     351 2001.47   511.5  1996.1   561.6 1992.21
   565.3 1992.31   580.3 1992.88   722.1 2005.24   752.2 2009.03   862.5 2018.88
   892.6 2022.94   932.7 2034.94   952.8 2043.24    1023 2061.07    1033 2065.28
  1093.2 2080.14  1103.2 2085.23  1133.3 2093.95  1153.4  2097.3  1243.6 2106.79
#Mann= 3 , 0 , 0
       0     .06       0   565.3    .045       0   580.3     .06       0
Bank Sta=565.3,580.3
XS Rating Curve= 0 ,0
Exp/Cntr=0.3,0.1

Type RM Length L Ch R = 1 ,6496.2  ,752.6,756.4,760.3
XS GIS Cut Line= 2
     2198064.554      330837.037     2199277.259        330896.6
#Sta/Elev= 30
       0 2095.32    20.1 2083.54    70.2 2063.88    90.3 2051.89   150.5  2025.7
   170.6 2011.35   190.6 2003.64   200.7 2001.81   240.8 1996.71     281    1994
   551.9 1993.43   602.1 1991.46   620.5 1988.65   632.2 1988.02   635.5 1988.17
   652.2 1989.63   682.3 1995.75   742.6  2004.1   752.6 2006.77   762.6 2012.34
   822.8 2031.84   832.9 2038.28     863 2047.69     883 2051.12   983.4 2061.15
  1083.7 2066.73  1093.8 2071.49  1103.8 2072.47    1174 2070.95  1214.2 2065.78
#Mann= 3 , 0 , 0
       0     .06       0   620.5    .045       0   635.5     .06       0
Bank Sta=620.5,635.5
XS Rating Curve= 0 ,0
Exp/Cntr=0.3,0.1