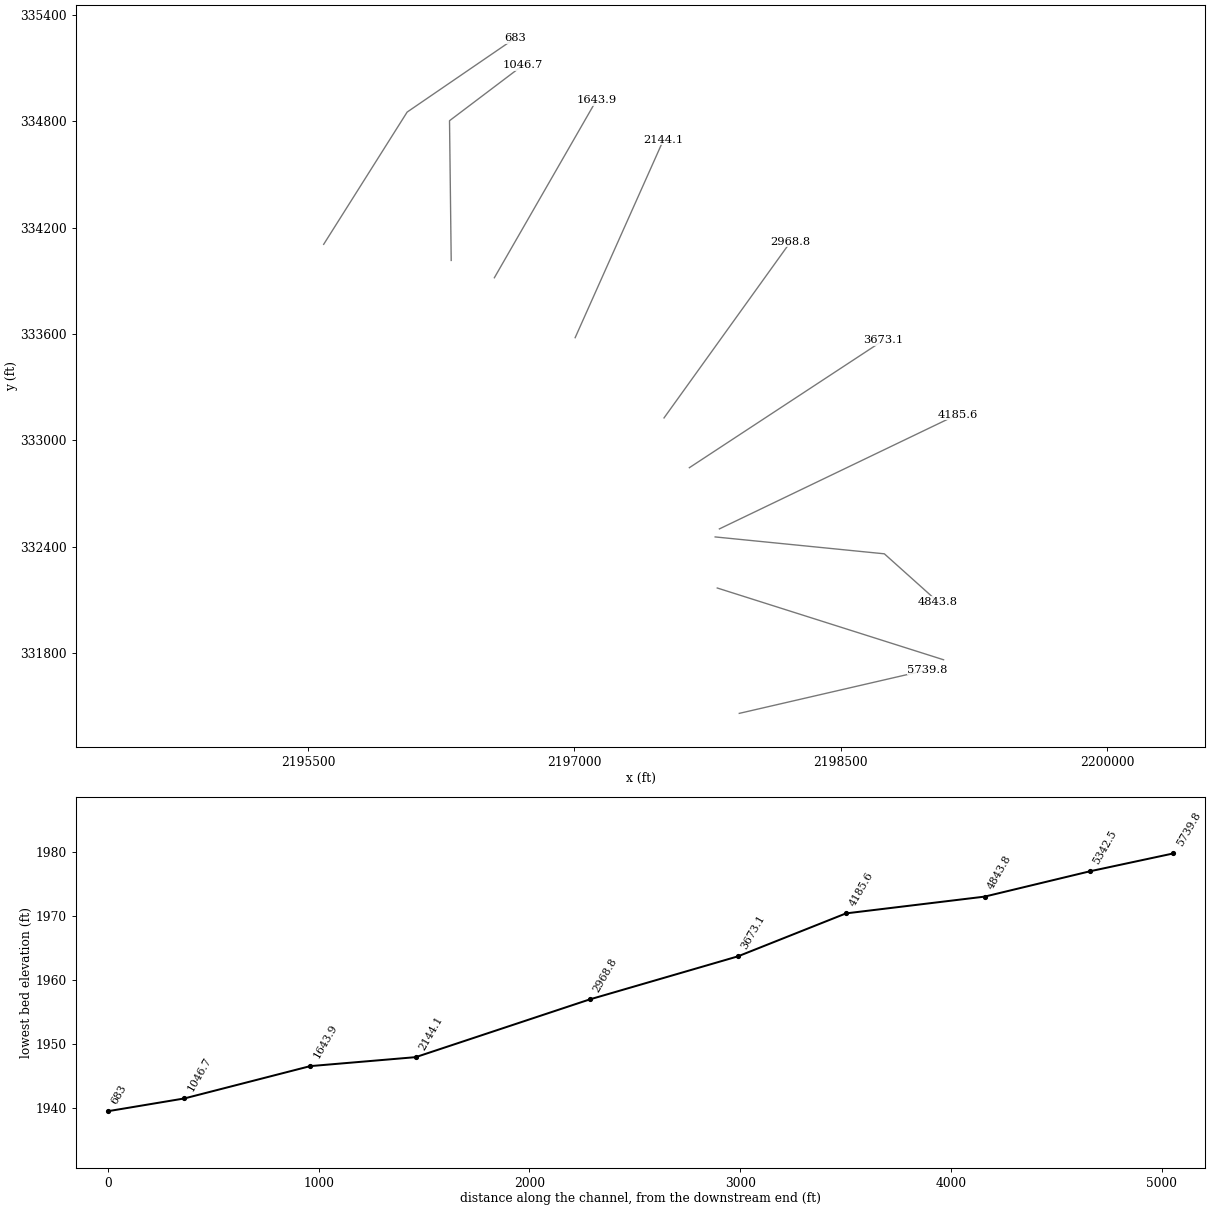
HEC-RAS study AntCkT2.prj: AntCkT2

--- AntCkT2.g01 (geometry) --- (continued)

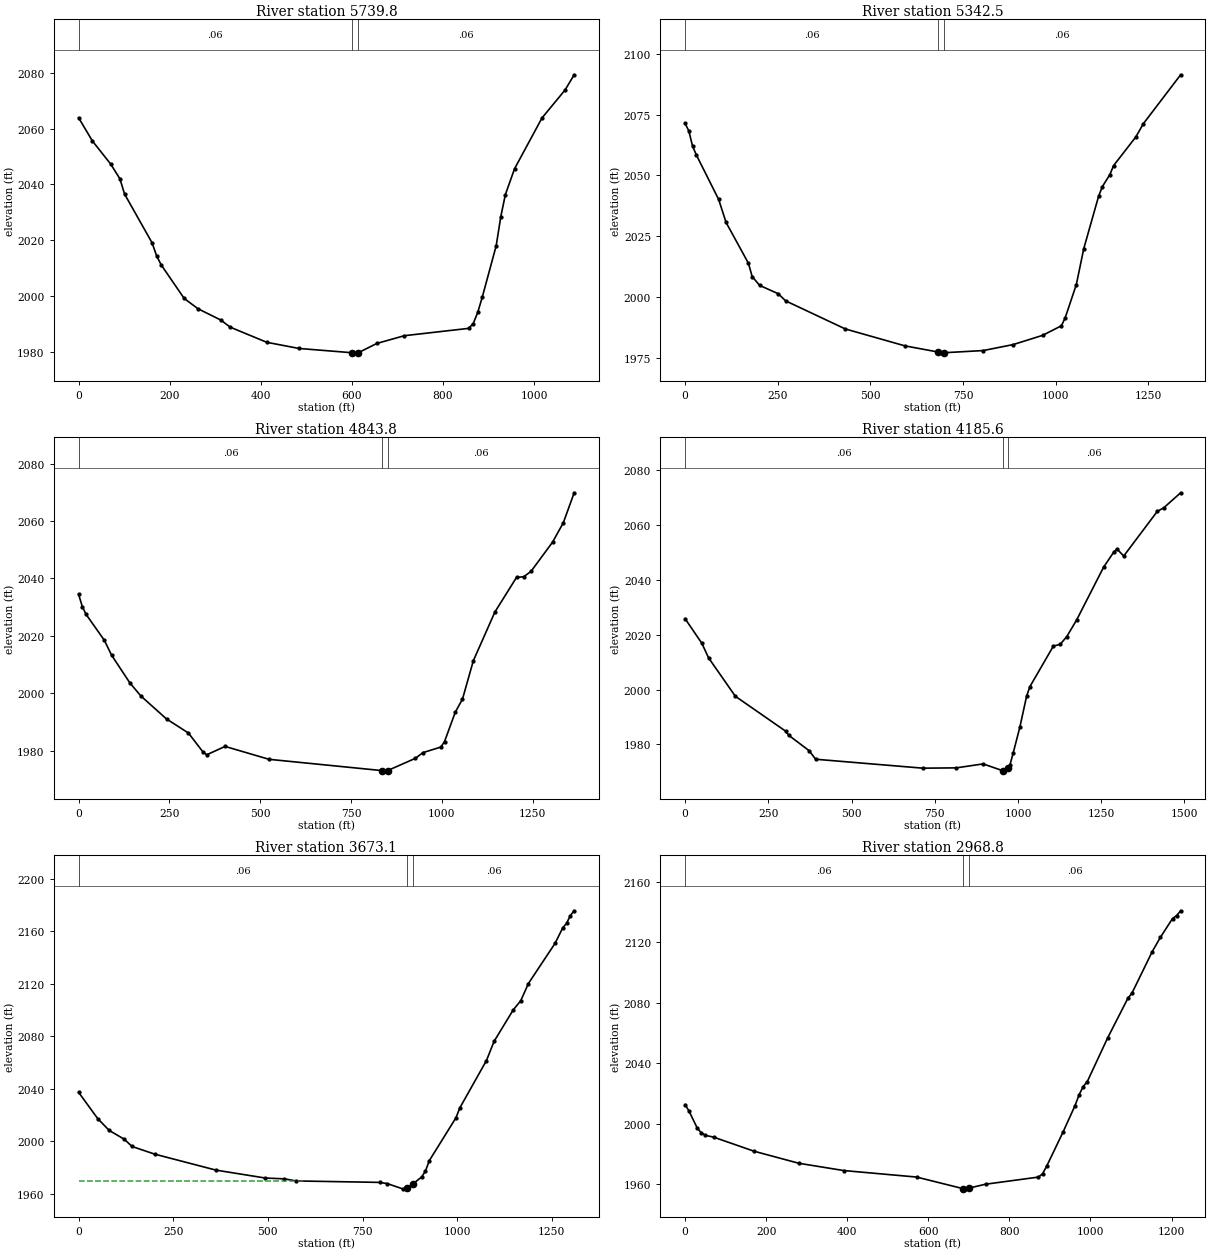
Type RM Length L Ch R = 1 ,5739.8  ,410.9,397,383.5
XS GIS Cut Line= 2
      2197928.75      331458.876     2198988.973      331704.276
#Sta/Elev= 30
       0 2063.82    30.2 2055.55    70.5 2047.26    90.7    2042   100.8 2036.58
   161.2 2019.14   171.3 2014.45   181.4  2011.2   231.8 1999.23     262 1995.56
   312.4 1991.49   332.5 1988.99   413.1 1983.55   483.7 1981.35   599.5 1979.83
   604.6 1979.78   614.5 1979.85     655 1983.15   715.4 1985.91   856.5 1988.53
   866.6 1990.26   876.6 1994.32   886.7 1999.87     917 2018.11     927 2028.43
   937.1 2036.36   957.3 2045.62  1017.7 2063.81  1068.1 2073.75  1088.2 2079.21
#Mann= 3 , 0 , 0
       0     .06       0   599.5    .045       0   614.5     .06       0
Bank Sta=599.5,614.5
XS Rating Curve= 0 ,0
Exp/Cntr=0.3,0.1

Type RM Length L Ch R = 1 ,5342.5  ,492.7,498.4,503.5
XS GIS Cut Line= 2
     2197804.859      332166.486     2199079.509      331761.457
#Sta/Elev= 30
       0 2071.38    10.1 2068.28    20.1 2062.05    30.2 2058.47    90.5 2040.13
   110.6 2030.64     171 2013.82     181 2008.38   201.1 2004.74   251.4  2001.3
   271.5 1998.36   432.4 1986.81   593.3 1979.85   683.7 1977.29   693.9 1976.98
   698.7 1977.02   804.5 1977.92   884.9 1980.36   965.4  1984.2  1015.7 1988.14
  1025.7 1991.34  1055.9 2005.09    1076  2019.9  1116.2 2041.54  1126.3 2045.42
  1146.4 2050.34  1156.4 2054.02  1216.8 2065.91  1236.9  2071.3  1337.4 2091.41
#Mann= 3 , 0 , 0
       0     .06       0   683.7    .045       0   698.7     .06       0
Bank Sta=683.7,698.7
XS Rating Curve= 0 ,0
Exp/Cntr=0.3,0.1

Type RM Length L Ch R = 1 ,4843.8  ,645.2,657.7,670.3
XS GIS Cut Line= 3
     2197792.946      332454.771     2198745.956       332359.47
     2199048.536      332087.862
#Sta/Elev= 30
       0 2034.44    10.1 2030.22    20.2 2027.55    70.6 2018.52    90.7  2013.3
   141.1 2003.64   171.4 1999.08     242 1991.09   302.4 1986.19   342.8 1979.52
   352.9 1978.63   403.3 1981.53   524.2 1977.04   835.7 1973.11   846.9 1973.03
   850.7 1973.13   927.5  1977.4   947.7 1979.36   997.4 1981.31  1007.4  1983.2
  1037.1 1993.46  1056.9    1998  1086.7 2011.34  1146.2 2028.34  1205.7 2040.38
  1225.5 2040.61  1245.4 2042.44  1304.9 2052.64  1334.6 2059.42  1364.4 2069.83
#Mann= 3 , 0 , 0
       0     .06       0   835.7    .045       0   850.7     .06       0
Bank Sta=835.7,850.7
XS Rating Curve= 0 ,0
Exp/Cntr=0.3,0.1

Type RM Length L Ch R = 1 ,4185.6  ,509.4,512.4,515.4
XS GIS Cut Line= 2
     2197816.771      332500.039     2199158.133      333145.703
#Sta/Elev= 30
       0 2025.78    50.3 2016.84    70.4 2011.56   150.9 1997.56   301.8 1984.87
   311.8 1983.31   372.2 1977.78   392.3 1974.63   714.2 1971.38   814.7 1971.49
   895.2 1972.93   954.8 1970.44   955.6 1970.41   969.8 1971.32   975.7 1972.46
   985.7 1976.92  1005.9 1986.43    1026 1997.61    1036 2001.09  1106.4 2015.82
  1126.6 2016.44  1146.7 2019.27  1176.8 2025.45  1257.3 2044.54  1287.5 2049.98
  1297.6 2051.15  1317.7 2048.59  1418.3  2064.8  1438.4 2066.19  1488.7 2071.61
#Mann= 3 , 0 , 0
       0     .06       0   954.8    .045       0   969.8     .06       0
Bank Sta=954.8,969.8
XS Rating Curve= 0 ,0
Exp/Cntr=0.3,0.1

Type RM Length L Ch R = 1 ,3673.1  ,694.3,704.1,713.9
XS GIS Cut Line= 2
     2197647.612      332845.505     2198741.191      333565.028
#Sta/Elev= 30
       0 2037.26    50.4 2017.26    80.6 2008.26   120.8 2001.47     141 1996.01
   201.4 1990.12   362.5 1977.99   493.4 1971.93   543.8 1971.31     574 1969.73
   795.5 1968.61   815.6 1967.67   855.9  1963.7   868.5 1964.39   883.5  1967.5
   906.3 1972.82   916.3 1977.29   926.4  1985.2   996.9 2017.93    1007 2025.42
  1077.4 2061.54  1097.6 2076.18  1147.9 2100.03  1168.1 2107.21  1188.2 2120.24
  1258.7 2150.92  1278.8 2162.61  1288.9 2166.08    1299 2172.04  1309.1 2175.69
#Mann= 3 , 0 , 0
       0     .06       0   868.5    .045       0   883.5     .06       0
#XS Ineff= 2 , 0
          601.37 1969.92
Permanent Ineff=
       F       F
Bank Sta=868.5,883.5
XS Rating Curve= 0 ,0
Exp/Cntr=0.3,0.1

Type RM Length L Ch R = 1 ,2968.8  ,819.7,824.5,829.3
XS GIS Cut Line= 2
     2197504.912      333126.455     2198217.287      334119.967
#Sta/Elev= 30
       0  2012.7      10 2008.24    30.1 1997.07    40.1 1993.98    50.1 1992.33
    70.1 1991.19   170.4 1981.82   280.6 1973.87   390.8 1969.08   571.2 1964.75
   684.4 1957.17   691.4 1956.96   699.4 1957.39   741.5 1960.03   871.8 1964.74
   881.8 1966.91   891.8 1971.82   931.9 1994.25     962 2012.07     972 2019.21
     982 2024.58     992  2027.8  1042.1 2056.64  1092.2 2082.96  1102.3 2086.36
  1152.4  2113.9  1172.4 2123.29  1202.5 2135.78  1212.5  2137.7  1222.5 2140.92
#Mann= 3 , 0 , 0
       0     .06       0   684.4    .045       0   699.4     .06       0
Bank Sta=684.4,699.4
XS Rating Curve= 0 ,0
Exp/Cntr=0.3,0.1

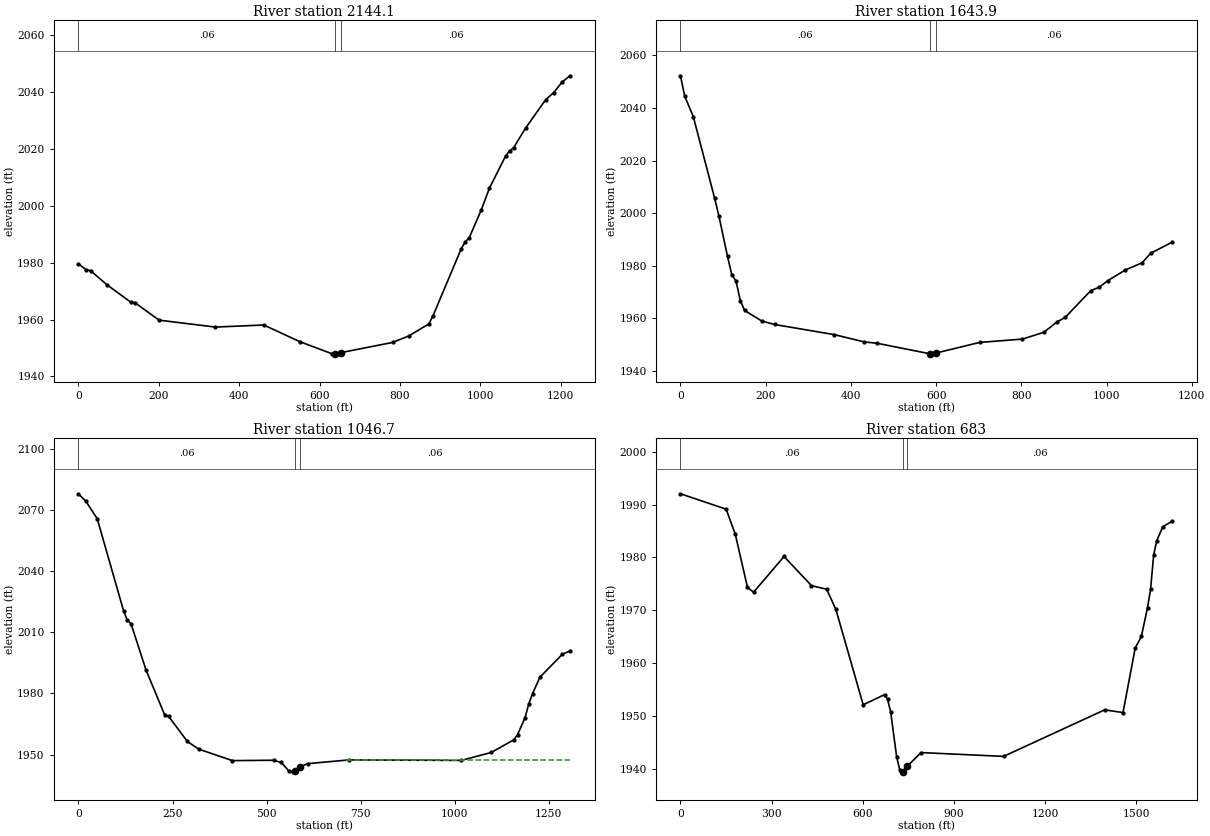
Type RM Length L Ch R = 1 ,2144.1  ,502.4,500.1,497.8
XS GIS Cut Line= 2
      2197004.33      333579.323     2197502.278      334696.727
#Sta/Elev= 30
       0 1979.63      20 1977.41    30.1 1977.23    70.2 1972.32   130.4 1966.11
   140.4 1965.97   200.6  1959.8   340.9 1957.36   461.3 1958.09   551.5  1952.2
   631.7 1947.95   638.7 1948.02   653.7 1948.39   782.1 1951.96   822.2 1954.24
   872.4  1958.5   882.4 1961.31   952.6 1984.86   962.6 1987.28   972.6 1988.79
  1002.7 1998.58  1022.8 2006.18  1062.9 2017.45  1072.9 2019.33    1083 2020.41
    1113 2027.35  1163.2 2037.38  1183.2 2039.85  1203.3 2043.44  1223.3 2045.73
#Mann= 3 , 0 , 0
       0     .06       0   638.7    .045       0   653.7     .06       0
Bank Sta=638.7,653.7
XS Rating Curve= 0 ,0
Exp/Cntr=0.3,0.1

Type RM Length L Ch R = 1 ,1643.9  ,584.8,596.9,609.1
XS GIS Cut Line= 2
     2196549.268      333917.641     2197123.456      334918.302
#Sta/Elev= 30
       0 2052.24      10 2044.48    30.1  2036.7    80.3 2005.61    90.3 1998.87
   110.4 1983.56   120.4 1976.68   130.4 1974.18   140.4 1966.81   150.5 1963.05
   190.6 1959.04   220.7 1957.71   361.2 1953.85   431.4 1951.08   461.5 1950.57
     585 1946.58   591.9 1946.55     600 1946.87   702.2 1950.88   802.6 1952.16
   852.7 1954.72   882.8 1958.55   902.9  1960.4   963.1 1970.57   983.2  1971.9
  1003.2  1974.4  1043.3 1978.34  1083.5 1981.16  1103.5 1984.76  1153.7 1988.97
#Mann= 3 , 0 , 0
       0     .06       0     585    .045       0     600     .06       0
Bank Sta=585,600
XS Rating Curve= 0 ,0
Exp/Cntr=0.3,0.1

Type RM Length L Ch R = 1 ,1046.7  ,376.5,363.6,350.7
XS GIS Cut Line= 3
     2196306.251      334015.325      2196296.72      334803.941
     2196709.294      335116.448
#Sta/Elev= 30
       0 2078.14      20 2074.37    49.9 2065.92   119.8 2020.74   129.8 2016.04
   139.8 2014.25   179.7 1991.51   229.6 1969.29   239.6 1968.78   289.5 1956.43
   319.5 1952.66   409.3 1947.01   519.1  1947.2   539.1 1946.09   559.1 1941.96
     569  1941.5   574.7 1942.07   589.7 1943.97     609 1945.53   718.8 1947.36
  1017.6 1947.12  1097.2 1951.03  1156.9 1957.24  1166.9 1959.78  1186.8 1968.07
  1196.8 1974.88  1206.7 1979.89  1226.6 1988.05  1286.3 1999.32  1306.2 2000.86
#Mann= 3 , 0 , 0
       0     .06       0   574.7    .045       0   589.7     .06       0
#XS Ineff= 2 , 0
          521.19 1946.69  710.42         1947.25
Permanent Ineff=
       F       F
Bank Sta=574.7,589.7
XS Rating Curve= 0 ,0
Exp/Cntr=0.3,0.1

Type RM Length L Ch R = 1 ,683     ,680.4,683,685.5
XS GIS Cut Line= 3
     2195587.919      334106.258     2196058.071      334852.782
      2196664.82       335268.93
#Sta/Elev= 30
       0 1992.04   150.4 1989.13   180.5 1984.38   220.6 1974.35   240.6 1973.44
   340.9 1980.19   431.1 1974.69   481.2    1974   511.3 1970.23   601.5 1952.17
   671.7 1954.09   681.7 1953.21   691.8 1950.85   711.8 1942.26   721.8  1939.9
   731.6 1939.51   731.9  1939.5   746.6 1940.58     792 1943.14  1063.6 1942.42
  1396.2 1951.21  1456.7  1950.7    1497 1962.91  1517.2 1965.08  1537.4 1970.53
  1547.4 1973.98  1557.5 1980.38  1567.6 1983.14  1587.8 1985.84    1618 1986.81
#Mann= 3 , 0 , 0
       0     .06       0   731.6    .045       0   746.6     .06       0
Bank Sta=731.6,746.6
XS Rating Curve= 0 ,0
Exp/Cntr=0.3,0.1

Chan Stop Cuts=-1
Use User Specified Reach Order=0
Composite Channel Slope=5